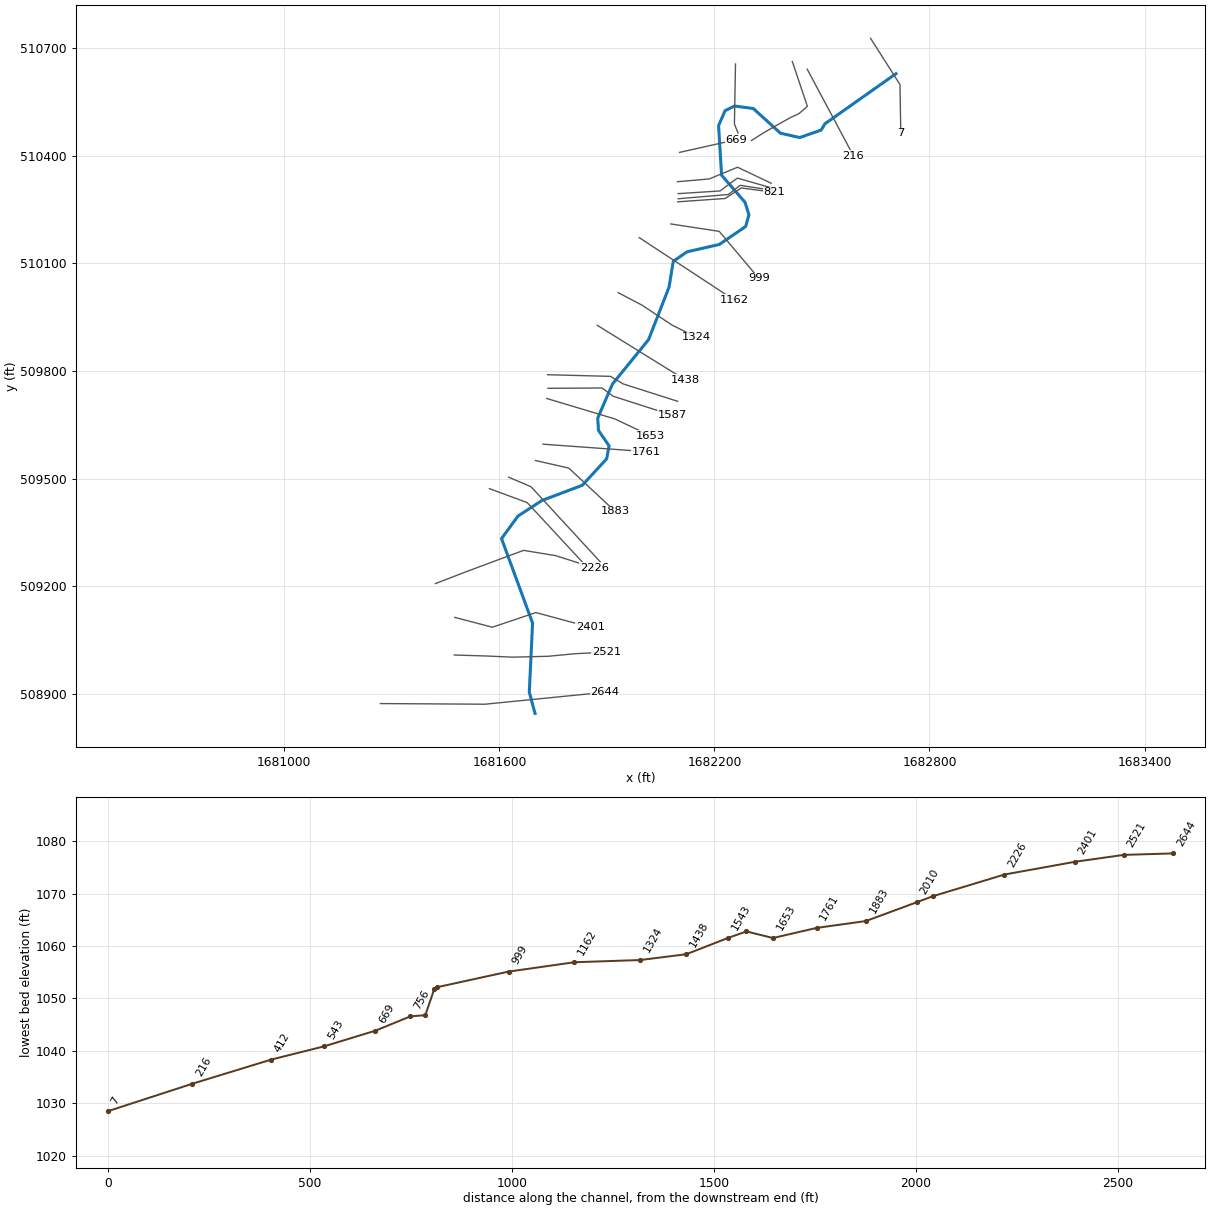
--- WhartonRn.prj (project) ---

Proj Title=WhartonRn
Current Plan=p01
Default Exp/Contr=0,0
English Units
Geom File=g01
Flow File=f01
Plan File=p01
BEGIN DESCRIPTION:
---------- MODELED AS PART OF WVEM CTP PROGRAM, 2025----------
Stream Name: Wharton Run
Flood Zone: AFH
Marshall County, WV
HEC-RAS Version: RAS 6.6
Vertical Datum: NAVD88
Projection: NAD 1983 StatePlane West Virginia N FIPS 4701 (US Feet)
Terrain: 1-meter West Virginia FEMA R3 South Central (collected 2018-2019)
Land Use: 2024 NLCD
Hydrologic Method:
Duda et al., "Estimation of magnitude and frequency of floods for rural, unregulated streams in and near Virginia and West Virginia." September 8, 2025.
Additional Model Notes:
None
END DESCRIPTION:
DSS Export Rating Curves= 0
DSS Export Rating Curve Sorted= 0
DSS Export Volume Flow Curves= 0
DXF OffsetX= 0
DXF OffsetY= 0
DXF ScaleX= 0
DXF ScaleY= 0

--- WhartonRn.p01 (plan) ---

Plan Title=Floodplain
Program Version=6.60
Short Identifier=Floodplain
Geom File=g01
Flow File=f01
Subcritical Flow
K Sum by GR= 0
Std Step Tol= 0.01
Critical Tol= 0.01
Num of Std Step Trials= 20
Max Error Tol= 0.3
Flow Tol Ratio= 0.001
Split Flow NTrial= 30
Split Flow Tol= 0.02
Split Flow Ratio= 0.02
Log Output Level= 0
Friction Slope Method= 1
Unsteady Friction Slope Method= 2
Unsteady Bridges Friction Slope Method= 1
Parabolic Critical Depth
Global Vel Dist= 0 , 0 , 0
Global Log Level= 0
CheckData=False
Encroach Param=-1 ,0,0, 0
Flow Ratio Tolerance=0.1
Flow Ratio Min Ratio=0.5
Flow Ratio Max Ratio=4
Flow Ratio Max Iterations= 10
Mapping Interval=1HOUR
Computation Time Step Use Courant=        0
Computation Time Step Use Time Series=    0
Computation Time Step Count To Double=0
Computation Time Step Max Doubling=0
Computation Time Step Max Halving=0
Computation Time Step Residence Courant=0
Run HTab= 0
Run UNet= 0
Run Sediment= 0
Run PostProcess= 0
Run WQNet= 0
Run RASMapper= 0
UNET Theta= 0
UNET Theta Warmup= 0
UNET ZTol= 0
UNET ZSATol= 0
UNET MxIter= 0
UNET Max Iter WO Improvement= 0
UNET MaxInSteps= 0
UNET DtIC= 0
UNET DtMin= 0
UNET MaxCRTS= 0
UNET WFStab= 0
UNET SFStab= 0
UNET WFX= 1
UNET SFX= 1
UNET Gravity=32.17405
UNET 1D Methodology=Finite Difference
UNET DSS MLevel= 1
UNET Pardiso=0
UNET DZMax Abort= 0
UNET Use Existing IB Tables= 0
UNET Froude Reduction=False
UNET Froude Limit= 0
UNET Froude Power= 0
UNET D1 Cores= 0
UNET WindReference=Eulerian
UNET WindDragFormulation=Hsu (1988)
UNET D2 Coriolis=0
UNET D2 Cores= 0
UNET D2 Theta= 1
UNET D2 Theta Warmup= 1
UNET D2 Z Tol= 0.01
UNET D2 Volume Tol= 0.01
UNET D2 Max Iterations= 20
UNET D2 Advanced Convergence=0
UNET D2 WS Max Tol=0.15
UNET D2 WS RMS Tol=0.002
UNET D2 WS Stall Tol=1
UNET D2 Equation= 0
UNET D2 RampUpFraction=0.1
UNET D2 TimeSlices= 1
UNET D2 Turbulence Formulation=Non-Conservative (original)
UNET D2 Eddy Viscosity=0.3
UNET D2 Transverse Eddy Viscosity=0.1
UNET D2 Smagorinsky Mixing=0
UNET D2 BCVolumeCheck=0
UNET D2 Cores=0
UNET D2 SolverType=PARDISO (Direct)
UNET D2 Minimum Iterations= 3
UNET D2 Maximum Iterations= 30
UNET D2 Restart Number= 10
UNET D2 Relaxation Coeff=1.3
UNET D2 SOR Precondition Iterations= 10
UNET D2 ILUT Maximum Fill= 8
UNET D2 ILUT Tolerance=1E-08
UNET D2 Convergence Tolerance=0.00001
PS Theta= 1
PS WS Tol= 0.01
PS Volume Tol= 0.01
PS Max Iterations= 20
PS Equation= 0
PS Advance Time Step=-1
PS Target Courant=0.9
PS Time Slices= 1
PS Iterate With 2D=0
PS Project Initial WSE from DS=-1
PS Ramp Up Initial WSE from US=-1
PS Cores=0
UNET D1D2 MaxIter= 0
UNET D1D2 ZTol=0.01
UNET D1D2 QTol=0.1
UNET D1D2 MinQTol=1
Write IC File= 0
Write IC File at Fixed DateTime=0
Write IC File at Sim End=0
Echo Input=False
Echo Parameters=False
Echo Output=False
Write Detailed= 0
HDF Write Warmup=0
HDF Write Time Slices=0
HDF Flush=0
HDF Compression= 1
HDF Chunk Size= 1
HDF Spatial Parts= 1
HDF Use Max Rows=0
HDF Fixed Rows= 1
Calibration Method= 0
Calibration Iterations= 20
Calibration Max Change=0.05
Calibration Tolerance=0.2
Calibration Maximum=1.5
Calibration Minimum=0.5
Calibration Optimization Method= 1
WQ AD Non Conservative
WQ ULTIMATE=-1
WQ Max Comp Step=1HOUR
WQ Output Interval=15MIN
WQ Output Selected Increments= 0
WQ Create Restart=0
WQ Fixed Restart=0
WQ System Summary=0
WQ Write To DSS=0
Sorting and Armoring Iterations= 10
XS Update Threshold= 0.02
Bed Roughness Predictor= 0
Processes Affected by Predictor=Sediment Only
Hydraulics Update Threshold= 0.02
Energy Slope Method= 1
Volume Change Method= 1
Sediment Retention Method= 0
Sediment TS Multiplier= 1
Warm Up Method= 0
XS Weighting Method= 0
Number of US Weighted Cross Sections= 1
Number of DS Weighted Cross Sections= 1
Upstream XS Weight=0
Main XS Weight=1
Downstream XS Weight=0
Number of DS XS's Weighted with US Boundary= 1
Upstream Boundary Weight= 1
Weight of XSs Associated with US Boundary= 0
Number of US XS's Weighted with DS Boundary= 1
Downstream Boundary Weight= 0.5
Weight of XSs Associated with DS Boundary= 0.5
Percentile Method= 0
Sediment Output Level= 3
Mass or Volume Output= 0
Output Increment Type= 1
Profile and TS Output Increment= 1
Transport Output Increment 1
XS Output Flag= 0
XS Output Increment= 10
Read HDF5 Sediment Hotstart= 0
Sediment Hotstart Type= 0
Write Gradation File= 0
Read Gradation Hotstart= 0
Write HDF5 File= 1
Write Binary Output= 1
Write DSS Sediment File= 0
DSS Sediment Output Type= 1
SV Curve= 0
Specific Gage Flag= 0
Subcell Erosion Methods= 0
Subcell Deposition Methods= 0
Advection Scheme= 1
Matrix Solver= 0
Implicit Weighting Factor= 1
Maximum Outer Loop Convergence Iterations= 5
Convergence Maximum Absolute= 0.001
Convergence RMSE= 0.0001
Grain Fractions Max Abs Error= 0.001
Max Subgrid Regions= 1
Max Subgrid Length Scale= 3.402823E+38
Initial Layer Thickness= 3
Min Layer Thickness= 0.1
Max Layer Thickness= 6
Number of Layers= 5

--- WhartonRn.f01 (steady flow) ---

Flow Title=Flow
Program Version=6.60
Number of Profiles= 1
Profile Names=P100yr
River Rch & RM=WhartonRn,Main            ,2644
     877
Boundary for River Rch & Prof#=WhartonRn,Main            , 1
Up Type= 0
Dn Type= 3
Dn Slope=0.03
DSS Import GetInterval= 0
DSS Import GetPeak= 0
DSS Import FillOption= 0

--- WhartonRn.g01 (geometry) ---

Geom Title=Geometry
Program Version=6.60

River Reach=WhartonRn       ,Main
Reach XY= 30
1681699.40720386508844.8382852741681683.44532919508904.111599847
     1681692.593      509096.759     1681606.019      509332.407
     1681651.852       509395.37     1681718.982      509438.889
     1681831.253       509481.15     1681899.259      509554.963
     1681906.074      509591.111     1681876.445       509634.37
      1681874.37      509668.741     1681915.449      509763.698
     1682016.204        509887.5     1682073.191      510033.677
     1682085.168      510106.169     1682123.852      510132.717
     1682213.547      510153.008     1682287.123      510203.259
     1682296.225      510235.875     1682285.227      510270.957
     1682219.907      510346.296     1682211.574      510484.722
      1682229.63      510526.389     1682256.019      510539.352
     1682308.333      510532.407     1682384.259      510463.426
     1682437.963      510451.389     1682497.685      510472.222
     1682508.333      510489.8151682706.51087545510629.575234969

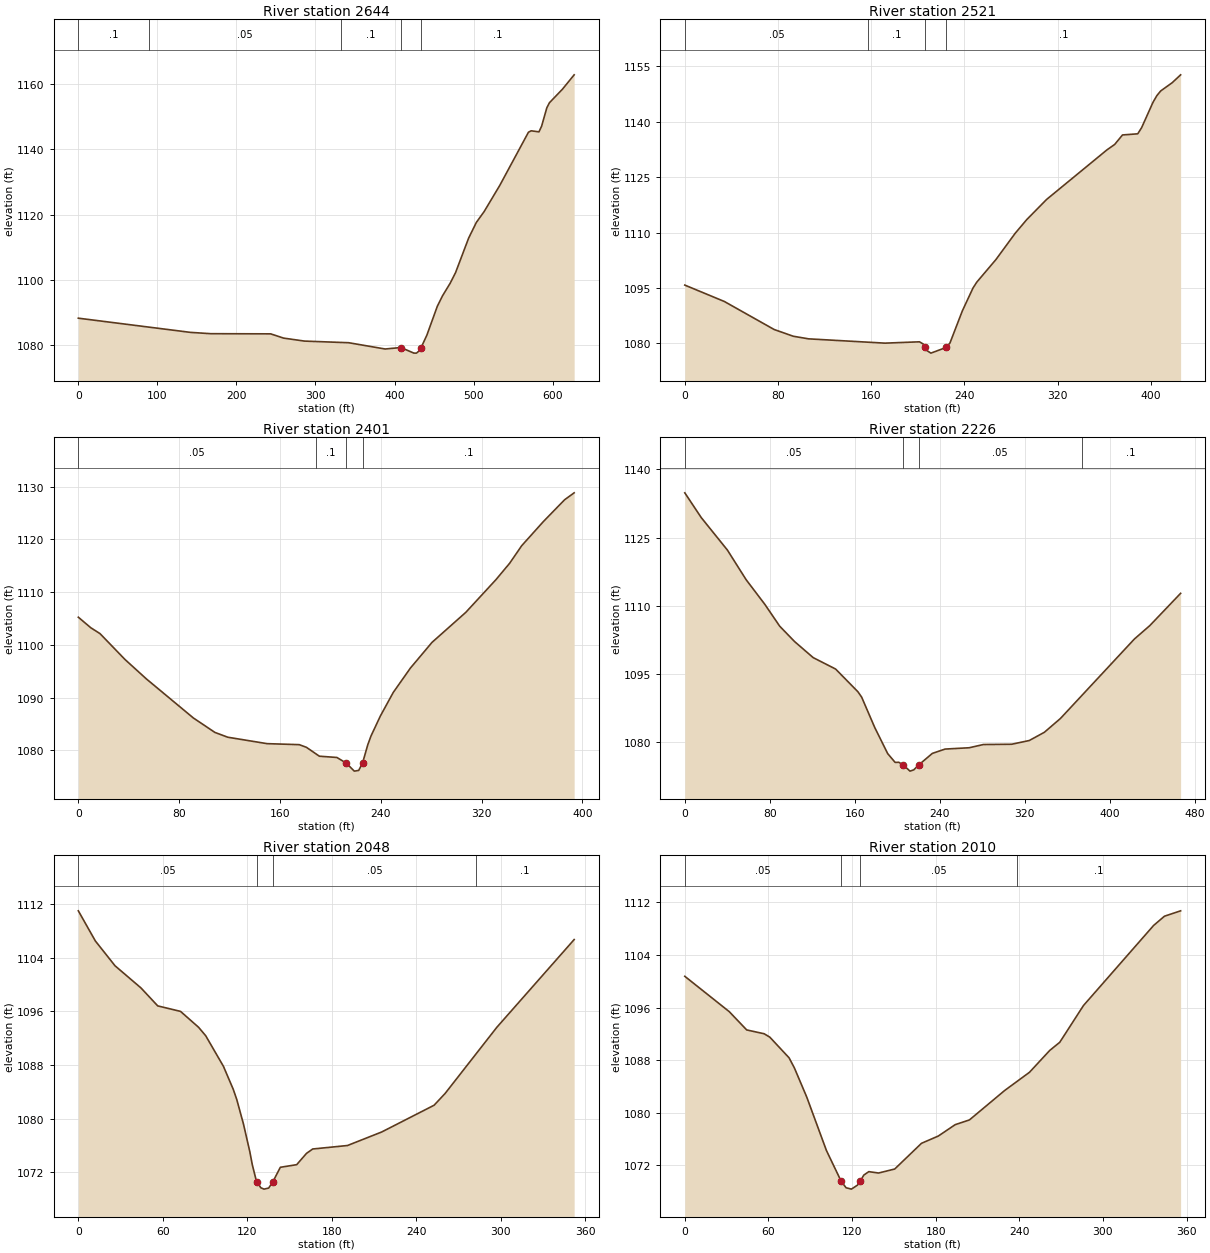
Type RM Length L Ch R = 1 ,2644    ,123.3,122.8,121.3
XS GIS Cut Line= 3
1681268.00818615508872.1940126771681559.88310332508870.414334106
1681893.56560017508903.654736091
#Sta/Elev= 30
       0 1088.34   141.6 1084.01   167.4  1083.6   243.3 1083.55   259.7 1082.25
     286 1081.34     342 1080.84   388.1 1078.92407.97731079.374   424.4 1077.67
   427.7 1077.66     431 1078.32433.47731079.288   440.9 1083.16   454.1 1091.97
   460.7 1095.18   470.5 1099.08   477.2 1102.28   493.7  1112.8   503.5 1117.62
   513.4 1120.95   533.2 1128.96   569.4 1145.18   572.8 1145.61   582.7 1145.29
     586 1146.99   592.6 1152.62   595.9 1154.18   612.3  1158.3   627.2 1162.72
#Mann= 5, -1 ,  0
       0     0.1       0      90    0.05       0  331.88     0.1       0
407.9773   0.045       0433.4773     0.1       0
Bank Sta=407.9773,433.4773
XS Rating Curve= 0 ,0
Exp/Cntr(USF)=0,0
Exp/Cntr=0.3,0.1

Type RM Length L Ch R = 1 ,2521    ,117.4,120.3,121
XS GIS Cut Line= 6
1681474.01618484509007.6758518371681561.61148208509005.015096009
1681636.72091192509001.6509295111681736.68888783509004.182092428
1681811.53158592509011.3415269261681899.16526893509015.503920168
#Sta/Elev= 30
       0 1095.78      34 1091.34    76.7 1083.77    93.1 1081.95   106.3 1081.24
   171.9 1080.08   201.5 1080.44   204.8 1079.82  206.431078.923   208.1 1078.02
   211.3 1077.38  224.521078.926   227.7 1080.15   238.3 1088.81   247.4 1094.96
   250.7 1096.58   267.1 1102.67   283.6 1109.76   293.5 1113.46   310.6 1118.93
   362.4 1132.33   369.1 1133.82   375.8 1136.38   388.9 1136.69   392.2 1138.34
     402 1145.22   405.3 1147.02   408.6 1148.28   418.5 1150.52   425.7 1152.64
#Mann= 4, -1 ,  0
       0    0.05       0  157.64     0.1       0  206.43   0.045       0
  224.52     0.1       0
Bank Sta=206.43,224.52
XS Rating Curve= 0 ,0
Exp/Cntr(USF)=0,0
Exp/Cntr=0.3,0.1

Type RM Length L Ch R = 1 ,2401    ,174.5,175,174.9
XS GIS Cut Line= 4
1681475.50362136509112.6857254991681580.33873531509085.198470012
1681701.79405026509126.1097339941681853.29357469509085.198470012
#Sta/Elev= 30
       0 1105.26     9.9 1103.26    17.2 1102.15      37 1097.25      54 1093.56
    91.3 1086.15   108.4 1083.41   118.6  1082.5   149.8 1081.28   175.3 1081.09
     181 1080.59   191.3  1078.9   205.2 1078.66   212.71077.583     219 1076.07
   222.5  1076.2  225.541077.583   229.7 1081.06   232.3 1082.75   239.7 1086.52
   249.9 1090.98   263.5  1095.6   280.7 1100.49   307.5 1106.18   331.5  1112.4
   342.3 1115.49   351.9 1118.83     369 1123.38   385.9 1127.53   393.5 1128.85
#Mann= 4, -1 ,  0
       0    0.05       0  188.38     0.1       0   212.7   0.045       0
  225.54     0.1       0
Bank Sta=212.7,225.54
XS Rating Curve= 0 ,0
Exp/Cntr(USF)=0,0
Exp/Cntr=0.3,0.1

Type RM Length L Ch R = 1 ,2226    ,185.3,177.8,169.2
XS GIS Cut Line= 6
1681421.43033201509206.8732880951681503.26153317509238.493303582
1681573.67871517 509264.815101341681667.47478743509299.634257421
1681756.59665643509285.0191291721681864.49473459509250.657321259
#Sta/Elev= 30
       0 1134.83    15.5 1129.38    40.1 1122.24    57.7 1115.73    75.3 1110.31
    89.3  1105.5   103.3 1102.12   120.8 1098.59   141.9 1096.08   162.9 1091.08
   166.4  1089.9   178.7 1083.23   190.9 1077.48   197.9 1075.55   201.4 1075.57
  205.561074.971   211.9 1073.63   215.4 1073.91  220.011074.972   232.9 1077.53
   244.9 1078.48   267.6 1078.77   280.9 1079.48   307.5 1079.54   324.1 1080.36
   338.3 1082.17   353.4  1085.2     423 1102.68   437.5 1105.63   466.5 1112.73
#Mann= 4, -1 ,  0
       0    0.05       0  205.56   0.045       0  220.01    0.05       0
  373.27     0.1       0
Bank Sta=205.56,220.01
XS Rating Curve= 0 ,0
Exp/Cntr(USF)=0,0
Exp/Cntr=0.3,0.1

Type RM Length L Ch R = 1 ,2048    ,38.1,38.3,38.4
XS GIS Cut Line= 3
1681572.13909273509471.8817387771681677.61344519509432.888190294
1681840.61926261509257.097602871
#Sta/Elev= 30
       0 1111.02    12.1 1106.52    26.1 1102.81    44.5 1099.51    56.4 1096.83
    72.6 1096.01    85.4 1093.64    90.5 1092.37   103.1  1087.8     110  1084.4
   112.5 1082.89   117.3  1079.2   121.8 1075.08   123.6  1073.1   126.2 1070.92
  126.931070.568   129.6 1069.69   131.9 1069.48   135.2 1069.64  138.171070.571
   143.5 1072.74   155.1 1073.13   162.1 1074.82   166.5 1075.47   191.2 1075.99
   215.5 1078.01   252.7    1082   260.5 1083.75   297.3 1093.64   352.2 1106.73
#Mann= 4, -1 ,  0
       0    0.05       0  126.93   0.045       0  138.17    0.05       0
  282.45     0.1       0
Bank Sta=126.93,138.17
XS Rating Curve= 0 ,0
Exp/Cntr(USF)=0,0
Exp/Cntr=0.3,0.1

Type RM Length L Ch R = 1 ,2010    ,126.1,126.8,125.8
XS GIS Cut Line= 3
1681625.86672179509503.7576343281681688.37004176 509477.05167034
1681883.33778418509265.463726933
#Sta/Elev= 30
       0 1100.75    31.9 1095.37    44.4 1092.59    56.9 1092.01      61 1091.49
    74.8 1088.35    78.6 1086.82    87.5 1082.37   101.6 1074.25  112.15 1069.58
   115.7 1068.58   119.5 1068.37   123.9 1068.98  125.861069.579   128.4  1070.5
     132 1071.03     139 1070.82   150.6 1071.43   169.8 1075.34   181.9 1076.45
     194 1078.18   204.2  1078.9   229.5 1083.38   247.3 1086.15   261.8 1089.47
     269 1090.71     286  1096.3   336.3 1108.48   344.1 1109.89   355.7 1110.71
#Mann= 4, -1 ,  0
       0    0.05       0  112.15   0.045       0  125.86    0.05       0
  237.97     0.1       0
Bank Sta=112.15,125.86
XS Rating Curve= 0 ,0
Exp/Cntr(USF)=0,0
Exp/Cntr=0.3,0.1

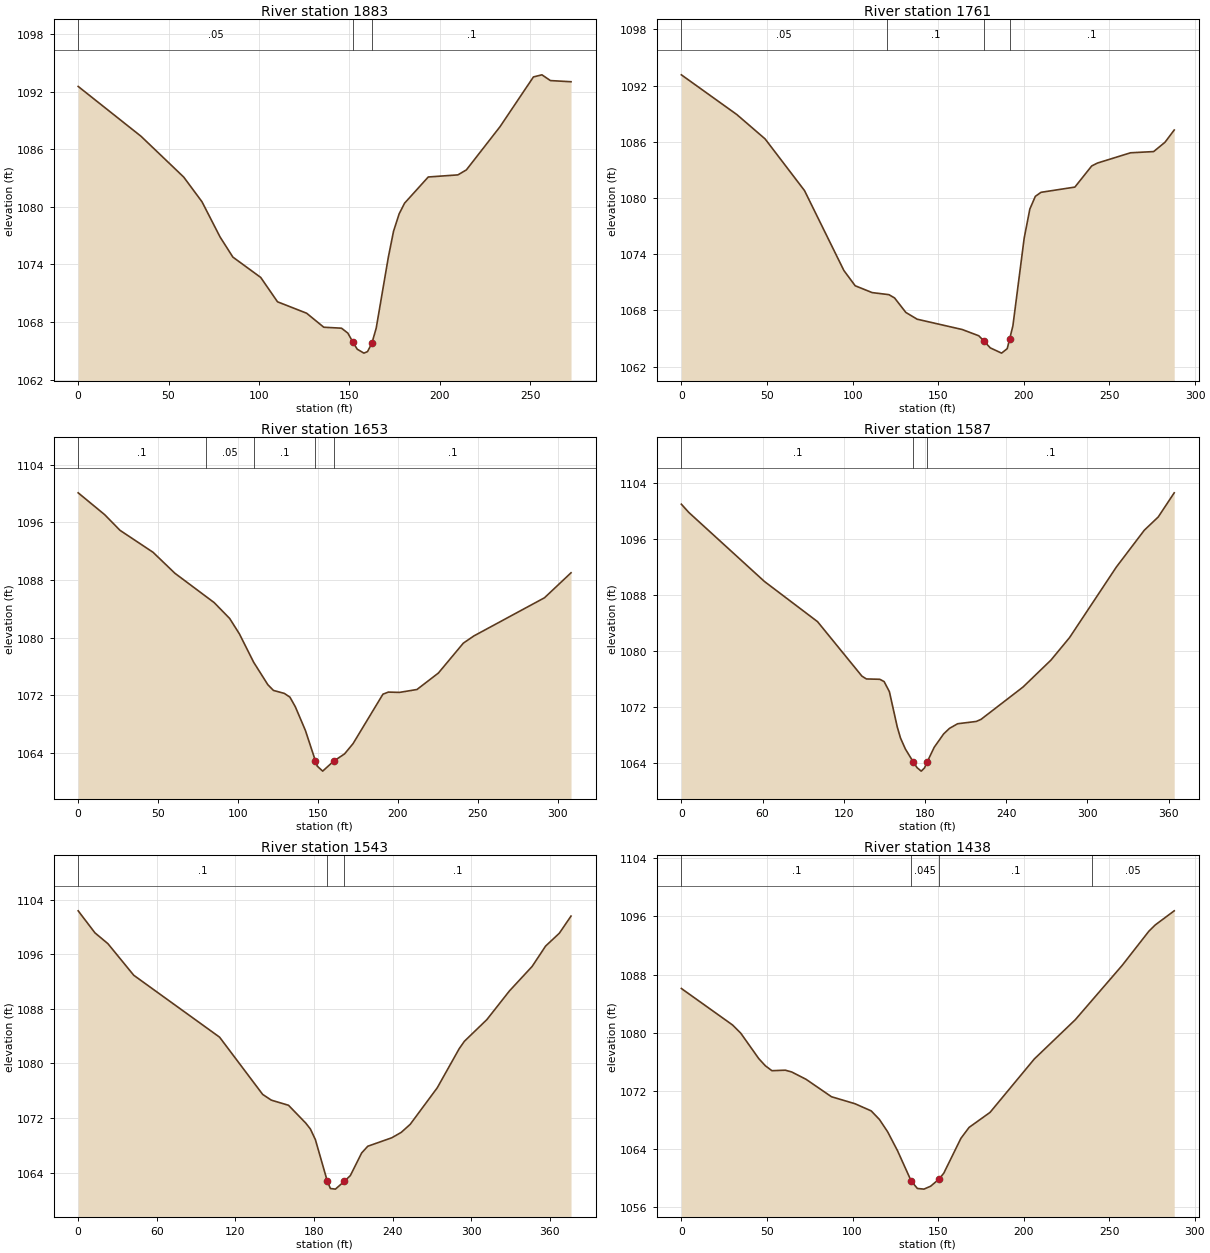
Type RM Length L Ch R = 1 ,1883    ,115.2,121.9,125.1
XS GIS Cut Line= 3
1681700.48956312509550.4079880391681793.69053637509529.121345998
1681923.13633257509408.305269551
#Sta/Elev= 30
       0 1092.56    34.8 1087.36    58.4 1083.11    68.5 1080.54    78.5 1076.87
    85.6 1074.77     101 1072.65   110.3 1070.11   126.4 1068.92   135.9 1067.46
   145.7 1067.36   149.2 1066.85   151.9 1065.94   154.4 1065.17   158.1 1064.76
   160.1 1064.92   162.51065.786   164.9 1067.36   171.6 1074.74   174.5 1077.47
   177.6 1079.28   180.6 1080.39   193.7 1083.12   210.1 1083.34   214.8 1083.86
   233.4 1088.36   251.9 1093.55   256.6 1093.77   261.3 1093.17   272.7 1093.05
#Mann= 3, -1 ,  0
       0    0.05       0   151.9   0.045       0   162.5     0.1       0
Bank Sta=151.9,162.5
XS Rating Curve= 0 ,0
Exp/Cntr(USF)=0,0
Exp/Cntr=0.3,0.1

Type RM Length L Ch R = 1 ,1761    ,107.2,108.2,106.2
XS GIS Cut Line= 2
1681721.77620516509595.8578453691682008.85821538509575.146517978
#Sta/Elev= 30
       0 1093.15    32.4 1088.91    48.9 1086.31    71.9  1080.8    94.9 1072.27
   101.5 1070.64   111.4 1069.91   121.2 1069.69   124.5 1069.34   131.1 1067.79
   137.7 1067.07     164 1065.97   173.7  1065.3   176.7 1064.74   180.4 1064.01
     187 1063.45   190.3 1063.93   191.71064.961   193.6 1066.36   200.2 1075.73
   203.5 1078.83   206.7 1080.18     210 1080.61   229.8 1081.17   239.6 1083.42
   242.9 1083.73   262.3 1084.83   275.8 1084.96   282.4 1085.95   287.8 1087.26
#Mann= 4, -1 ,  0
       0    0.05       0     120     0.1       0   176.7   0.045       0
   191.7     0.1       0
Bank Sta=176.7,191.7
XS Rating Curve= 0 ,0
Exp/Cntr(USF)=0,0
Exp/Cntr=0.3,0.1

Type RM Length L Ch R = 1 ,1653    ,67.4,65.6,63.6
XS GIS Cut Line= 3
1681732.24039966509723.4108782271681921.61111992509666.520049127
1682021.71586898509619.344247848
#Sta/Elev= 30
       0 1100.08    16.6 1097.05    26.2 1094.88    46.8 1091.85    60.5 1088.94
    85.1 1084.87    94.8 1082.67   100.9 1080.53   109.8 1076.61   118.7 1073.49
   122.2  1072.7     129 1072.29   132.5 1071.77   135.9 1070.43   142.2 1067.15
  148.481062.925   149.6 1062.21     153 1061.52   159.8 1062.89   166.7 1063.91
     172 1065.33   190.7 1072.18   194.1 1072.47   201.1 1072.43     212 1072.83
   225.4 1075.11     241 1079.25   247.6 1080.25   291.8 1085.54   308.4    1089
#Mann= 5, -1 ,  0
       0     0.1       0      80    0.05       0     110     0.1       0
  148.48   0.045       0   159.8     0.1       0
Bank Sta=148.48,159.8
XS Rating Curve= 0 ,0
Exp/Cntr(USF)=0,0
Exp/Cntr=0.3,0.1

Type RM Length L Ch R = 1 ,1587    ,43.2,44.4,44
XS GIS Cut Line= 4
1681735.48373956509751.7673222271681886.51505864509752.660200378
1681917.04167878509729.770415187 1682083.5277947 509676.29456336
#Sta/Elev= 30
       0 1101.03     5.5 1099.85    61.3 1089.97   100.6  1084.2   133.4 1076.39
   136.7 1075.99   146.6 1075.94   149.8 1075.61   153.7 1074.16   159.5 1069.11
   161.9 1067.52   165.5 1065.95  171.261064.118   174.2 1063.26   177.2 1062.78
   179.6 1063.23  181.661064.117   186.8  1066.2   193.8 1068.12   198.1 1068.91
   204.1 1069.57   217.9  1069.9   221.4  1070.2   252.4 1074.83     273 1078.68
   286.8 1081.92   321.3 1092.01     342  1097.3   352.3  1099.2   364.1 1102.66
#Mann= 3, -1 ,  0
       0     0.1       0  171.26   0.045       0  181.66     0.1       0
Bank Sta=171.26,181.66
XS Rating Curve= 0 ,0
Exp/Cntr(USF)=0,0
Exp/Cntr=0.3,0.1

Type RM Length L Ch R = 1 ,1543    ,103.7,104.3,103.8
XS GIS Cut Line= 4
 1681734.7109066509789.6787535721681909.91186185509785.104523388
1681945.21385914509764.0886819531682097.34244895509715.479883393
#Sta/Elev= 30
       0 1102.39    12.8 1099.16    22.7 1097.57    42.4 1092.94   107.9 1083.86
   140.8 1075.46   147.4 1074.62   160.5 1073.87   173.6 1071.27   177.2 1070.39
     181 1068.84  190.191062.695   192.5 1061.66   196.3 1061.57     2031062.695
   207.7 1063.56   216.3 1066.87     221 1067.86   239.3  1069.1   246.5 1069.89
   253.4 1071.08     274 1076.43   290.8 1082.18   294.7 1083.25   311.9 1086.44
   329.1 1090.64   346.4 1094.23   356.7 1097.22   367.2 1099.11   376.1 1101.62
#Mann= 3, -1 ,  0
       0     0.1       0  190.19   0.045       0     203     0.1       0
Bank Sta=190.19,203
XS Rating Curve= 0 ,0
Exp/Cntr(USF)=0,0
Exp/Cntr=0.3,0.1

Type RM Length L Ch R = 1 ,1438    ,115,114.6,113.5
XS GIS Cut Line= 2
1681873.13955162509927.4942529031682117.78638485509775.795678895
#Sta/Elev= 30
       0 1086.08    29.9 1081.05    34.7 1079.92    45.2 1076.42    49.1 1075.42
    52.9 1074.75    60.7 1074.82    64.5 1074.57    72.8 1073.57    87.7 1071.16
   101.4  1070.2   110.9 1069.21   115.7 1068.03   120.5 1066.33   126.3 1063.71
   134.31059.524   137.9 1058.52   141.7 1058.43   145.6 1058.83   150.51059.808
   153.3 1060.63   163.3 1065.43   168.1 1066.94   180.3    1069   206.2 1076.37
   230.1 1081.77   257.5 1089.26   273.1 1093.97   276.8 1094.83   287.9 1096.78
#Mann= 4, -1 ,  0
       0     0.1       0   134.3   0.045       0   150.5     0.1       0
     240    0.05       0
Bank Sta=134.3,150.5
XS Rating Curve= 0 ,0
Exp/Cntr(USF)=0,0
Exp/Cntr=0.3,0.1

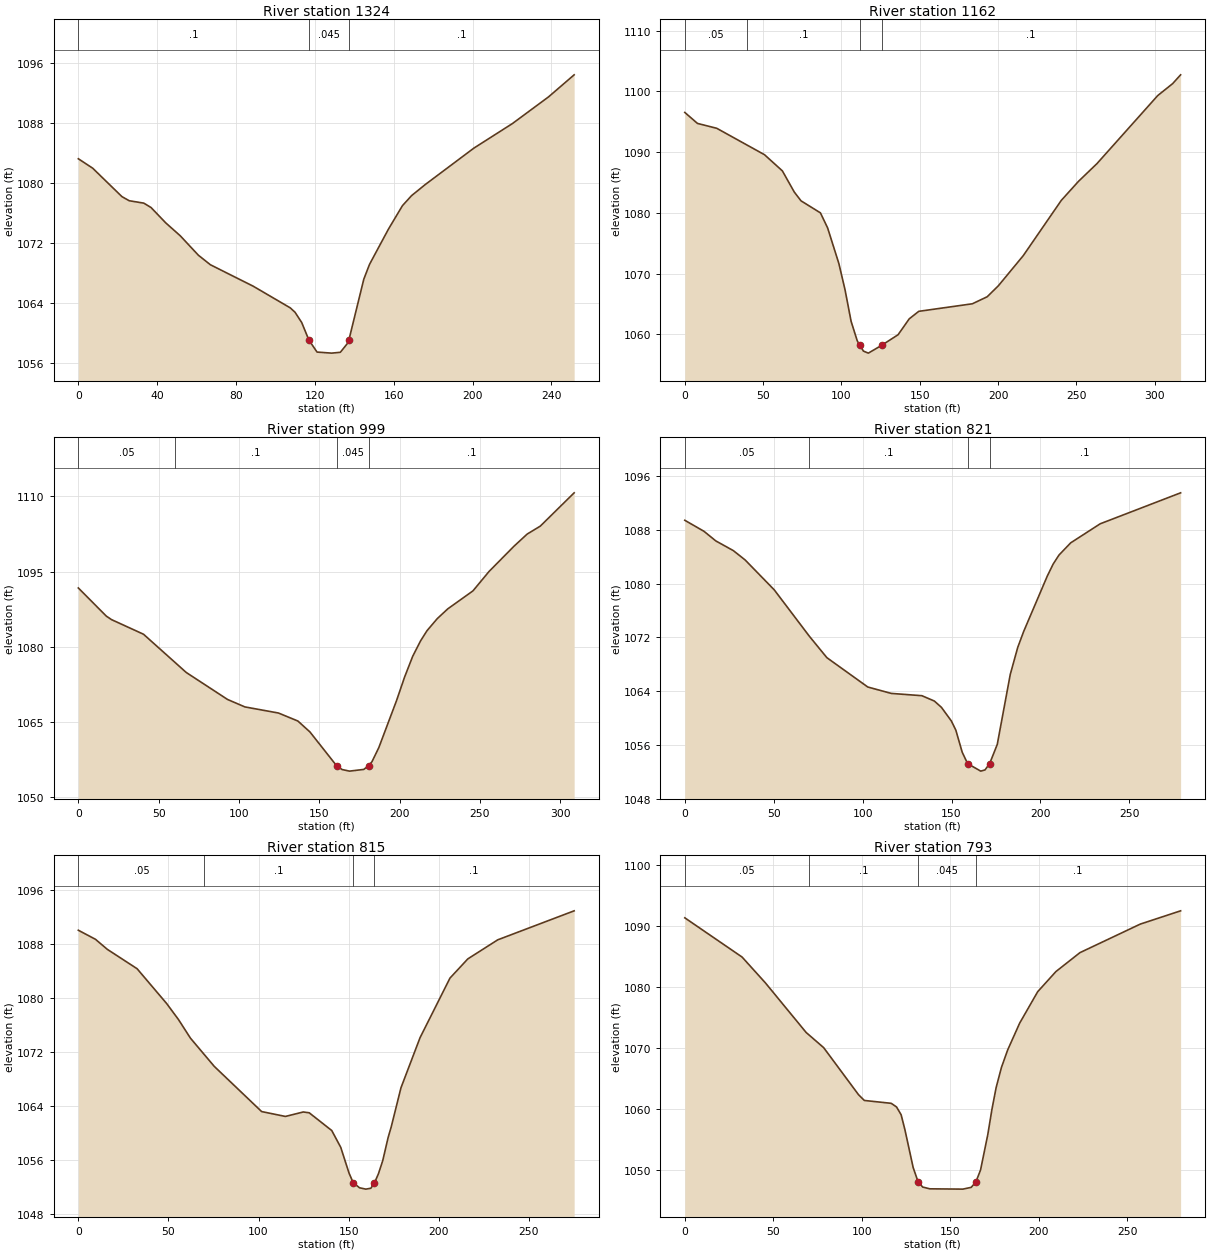
Type RM Length L Ch R = 1 ,1324    ,160.6,162.2,162.2
XS GIS Cut Line= 4
1681931.38895775510018.6908901781681998.02793209509983.692928672
1682081.69246292509928.1845095011682149.57782584509894.328606084
#Sta/Elev= 30
       0 1083.21     7.3 1081.95    22.1 1078.17    25.8 1077.62    33.2  1077.3
    36.9 1076.71    44.3 1074.68    51.7 1072.95    60.9 1070.36      67 1069.09
    88.6 1066.25   107.5 1063.35   109.9 1062.77   113.3  1061.4  116.971059.049
   121.1 1057.46   128.5 1057.32   132.9 1057.43   136.9 1058.74  137.221059.049
   144.8 1067.17   147.7 1069.14   157.2 1073.79   164.4 1076.96     169 1078.29
     176 1079.78   200.6 1084.62   220.2  1087.9   238.5 1091.45   251.5 1094.39
#Mann= 3, -1 ,  0
       0     0.1       0  116.97   0.045       0  137.22     0.1       0
Bank Sta=116.97,137.22
XS Rating Curve= 0 ,0
Exp/Cntr(USF)=0,0
Exp/Cntr=0.3,0.1

Type RM Length L Ch R = 1 ,1162    ,161.5,162.8,158.7
XS GIS Cut Line= 2
1681990.10663929510172.1873808431682254.75137818509998.442356619
#Sta/Elev= 30
       0 1096.52     8.1 1094.71    20.4 1093.91    50.9 1089.56    62.3  1086.9
    69.9 1083.42    74.2 1081.97    86.6 1079.99    91.2 1077.51    98.4 1071.63
   102.3 1067.35   106.2 1062.13   110.1 1058.94  111.691058.198   114.1 1057.23
   117.2  1056.9  125.791058.198   136.2 1059.93   143.3 1062.54   149.4 1063.78
   183.6 1065.02   193.1 1066.18   200.2 1067.98   216.1 1072.94   240.4 1082.04
   251.4 1085.18   263.2  1088.1     302  1099.3   311.5 1101.26   316.6 1102.71
#Mann= 4, -1 ,  0
       0    0.05       0      40     0.1       0  111.69   0.045       0
  125.79     0.1       0
Bank Sta=111.69,125.79
XS Rating Curve= 0 ,0
Exp/Cntr(USF)=0,0
Exp/Cntr=0.3,0.1

Type RM Length L Ch R = 1 ,999     ,166.3,178.3,189.5
XS GIS Cut Line= 3
1682078.12163561510210.3693242391682213.26304684510189.657996848
1682324.06864838510058.141067916
#Sta/Elev= 30
       0 1091.72    17.4  1086.1    20.7 1085.39    40.6 1082.47    67.2 1074.83
    92.9 1069.44   103.7 1067.95   124.6 1066.73   136.7 1065.13   144.2 1062.95
  160.741056.222   164.2 1055.44   168.8 1055.12   177.7 1055.46  180.721056.221
   182.8 1056.99   187.1 1059.83   198.1  1069.2   203.1 1073.89   208.2 1078.08
   213.1 1081.16   217.1 1083.19   223.5  1085.6     230 1087.54   245.7 1091.14
   255.7 1095.01   271.3 1100.08   279.5  1102.5   287.6 1104.07   308.7 1110.73
#Mann= 4, -1 ,  0
       0    0.05       0      60     0.1       0  160.74   0.045       0
  180.72     0.1       0
Bank Sta=160.74,180.72
XS Rating Curve= 0 ,0
Exp/Cntr(USF)=0,0
Exp/Cntr=0.3,0.1

Type RM Length L Ch R = 1 ,821     ,5.4,6,6.5
XS GIS Cut Line= 4
1682097.61356733510272.0682623611682229.95894936510281.388359686
1682274.69541652510310.7466662631682366.49837518510298.630539739
#Sta/Elev= 30
       0  1089.4    10.8 1087.76    17.4 1086.34    27.3 1084.89    33.9 1083.51
    50.3 1079.06      70 1072.18    79.9 1068.98   102.9 1064.62   116.1 1063.67
   133.3 1063.33   140.3 1062.54   144.3  1061.6   149.9 1059.57   152.4 1058.21
     156 1054.92  159.041053.234   166.4 1052.12   168.8  1052.3  171.411053.234
   175.7 1056.09     183 1066.48   187.2  1070.5   190.6 1072.91   203.8 1081.09
   207.1 1082.88   210.4 1084.23     217 1086.05   233.6 1088.88   278.8 1093.48
#Mann= 4, -1 ,  0
       0    0.05       0      70     0.1       0  159.04   0.045       0
  171.41     0.1       0
Bank Sta=159.04,171.41
XS Rating Curve= 0 ,0
Exp/Cntr(USF)=0,0
Exp/Cntr=0.3,0.1

Type RM Length L Ch R = 1 ,815     ,23.7,21.9,24.2
XS GIS Cut Line= 4
1682098.92309858510280.6235834441682238.98524625510292.455945624
1682271.45544944 510318.046868481682363.63780597510304.013136591
#Sta/Elev= 30
       0 1090.03     9.5 1088.69    16.1  1087.2    32.6 1084.34      49 1079.19
    55.6 1076.81    62.2 1074.07    75.4  1069.9   101.7 1063.21   114.9 1062.49
   124.8 1063.15   128.1 1063.03   140.6 1060.41   145.6 1057.92   150.2 1054.11
   152.5  1052.7     156 1051.94   159.5 1051.74   162.3 1051.87   164.2 1052.61
   166.5    1054   168.9 1055.96   171.9 1059.39   173.6 1060.94     179 1066.72
   189.6 1074.14   206.2 1082.95   216.1 1085.79   232.7 1088.61   275.1  1092.9
#Mann= 4, -1 ,  0
       0    0.05       0      70     0.1       0   152.5   0.045       0
   164.2     0.1       0
Bank Sta=152.5,164.2
XS Rating Curve= 0 ,0
Exp/Cntr(USF)=0,0
Exp/Cntr=0.3,0.1

Type RM Length L Ch R = 1 ,793     ,39.3,36.8,35.4
XS GIS Cut Line= 4
1682099.01158193510294.902500809 1682215.5127985 510302.35857867
 1682263.9773046510338.2409533751682363.23634112510309.814656531
#Sta/Elev= 30
       0 1091.38    32.4 1084.93    45.6 1080.68    68.6 1072.54    78.5 1070.05
    98.2 1062.32   101.5 1061.37   116.7  1060.9   119.7  1060.3   122.3 1059.02
   124.4 1056.61   129.1 1050.35  131.92 1047.97   134.5 1047.14   138.5 1046.85
   157.2  1046.8   161.9 1047.09  164.551047.973   167.2 1049.95   171.3 1055.78
   173.6 1059.86     176 1063.48     179 1066.79   182.5 1069.65   189.3 1074.07
   199.5 1079.24   209.8 1082.55   223.4 1085.66   257.5 1090.35   280.3 1092.53
#Mann= 4, -1 ,  0
       0    0.05       0      70     0.1       0  131.92   0.045       0
  164.55     0.1       0
Bank Sta=131.92,164.55
XS Rating Curve= 0 ,0
Exp/Cntr(USF)=0,0
Exp/Cntr=0.3,0.1

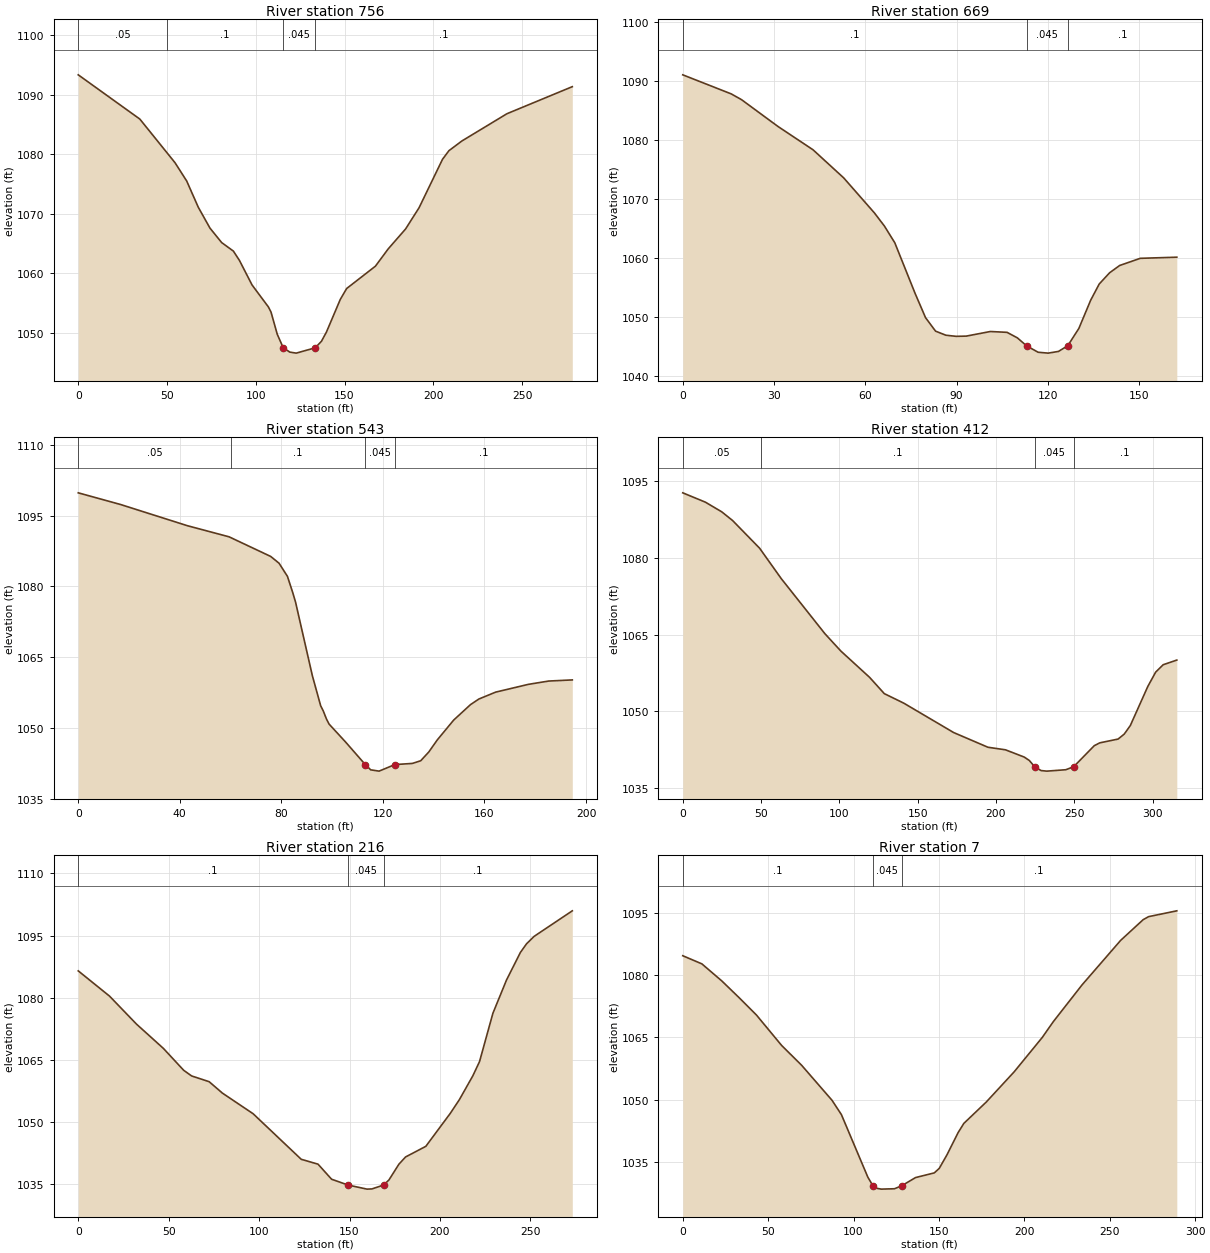
Type RM Length L Ch R = 1 ,756     ,89.2,86.5,85.1
XS GIS Cut Line= 4
 1682096.8048784510328.1958495821682185.54701399510335.864253375
1682264.53131951510368.5823158451682358.21307868510323.971423184
#Sta/Elev= 30
       0 1093.31    34.7 1085.88    54.5 1078.56    61.1 1075.48    67.6 1071.09
    74.2 1067.57    80.8 1065.14    87.4 1063.71    90.8 1062.15    97.9 1058.03
   107.1 1054.34   108.6 1053.47   112.1 1049.75  115.481047.472   119.2 1046.75
   122.8 1046.58  133.491047.474     137 1048.57   139.8 1050.11   147.6 1055.59
   151.2 1057.43   167.4 1061.18   174.6 1064.08   184.4 1067.43     192    1071
   205.2 1079.13   208.8 1080.57   216.1  1082.2   241.5 1086.78   278.3 1091.32
#Mann= 4, -1 ,  0
       0    0.05       0      50     0.1       0  115.48   0.045       0
  133.49     0.1       0
Bank Sta=115.48,133.49
XS Rating Curve= 0 ,0
Exp/Cntr(USF)=0,0
Exp/Cntr=0.3,0.1

Type RM Length L Ch R = 1 ,669     ,134.7,126.6,112.5
XS GIS Cut Line= 2
1682102.75188477510410.0290477041682261.19353931510445.445417542
#Sta/Elev= 30
       0 1091.11    15.9 1087.88    19.3  1086.9    31.3 1082.34    42.8 1078.39
    52.9 1073.61      63 1067.66    66.3 1065.42    69.7 1062.59    76.4 1053.96
    79.8 1049.88    83.1 1047.58    86.5 1046.89    89.9  1046.7    93.2 1046.74
   101.1 1047.52   106.6 1047.38     110 1046.44  113.011045.094   116.8    1044
   120.1 1043.85   123.5 1044.14  126.541045.095   130.2 1048.04   134.1 1052.85
   136.9 1055.59   140.3 1057.49   143.6 1058.73   150.4 1059.95   162.4 1060.14
#Mann= 3, -1 ,  0
       0     0.1       0  113.01   0.045       0  126.54     0.1       0
Bank Sta=113.01,126.54
XS Rating Curve= 0 ,0
Exp/Cntr(USF)=0,0
Exp/Cntr=0.3,0.1

Type RM Length L Ch R = 1 ,543     ,142.4,131,122.9
XS GIS Cut Line= 3
1682258.74129213510656.6912969341682255.77610022510488.989598607
  1682265.772041510464.042441039
#Sta/Elev= 30
       0 1099.85    16.7 1097.37      43 1092.88    59.4 1090.53    75.8 1086.37
    79.1 1084.93    82.4 1082.15    84.5 1078.69    85.6 1076.68    92.2 1061.13
    95.5  1054.7    96.5 1053.64    97.8 1051.88    98.8 1050.84   105.3 1047.04
  113.061042.259   115.2 1041.14   118.5 1040.87  124.711042.261   131.6  1042.5
   134.9 1043.07   138.1 1044.94   141.4 1047.47   147.9  1051.7   154.5 1054.96
   157.8 1056.15   164.4 1057.61   177.3 1059.26   185.3 1059.96   194.6  1060.2
#Mann= 4, -1 ,  0
       0    0.05       0      60     0.1       0  113.06   0.045       0
  124.71     0.1       0
Bank Sta=113.06,124.71
XS Rating Curve= 0 ,0
Exp/Cntr(USF)=0,0
Exp/Cntr=0.3,0.1

Type RM Length L Ch R = 1 ,412     ,166.7,195.5,204.5
XS GIS Cut Line= 6
1682417.30516952510663.5356949691682459.24560748510538.646390802
1682435.94536417510518.1421766851682410.78110139510506.492055027
1682338.55034711510465.4836267931682303.13397727510443.115393211
#Sta/Elev= 30
       0 1092.67    14.5 1090.84    24.9 1088.96    31.8 1087.27    49.1 1081.85
    62.9 1075.92    90.8 1065.16     101 1061.77   119.3 1056.65   128.7 1053.47
   141.2  1051.6     173 1045.87   194.9    1043   206.1  1042.5   218.1 1041.08
   221.3 1040.42  224.731039.194   228.8 1038.45   232.5 1038.34   244.6 1038.61
  249.631039.195   262.8 1043.31   266.3 1043.86     278  1044.6   281.9 1045.56
   285.8 1047.23     297 1054.88     302 1057.67   306.8 1059.11   315.5 1060.02
#Mann= 4, -1 ,  0
       0    0.05       0      50     0.1       0  224.73   0.045       0
  249.63     0.1       0
Bank Sta=224.73,249.63
XS Rating Curve= 0 ,0
Exp/Cntr(USF)=0,0
Exp/Cntr=0.3,0.1

Type RM Length L Ch R = 1 ,216     ,208,209.4,209.8
XS GIS Cut Line= 2
1682458.81630462510642.1406106121682587.49131031510401.184510228
#Sta/Elev= 30
       0 1086.47    17.3 1080.37    32.2 1073.61    47.1 1067.73    58.3 1062.45
    62.7 1061.08    72.4 1059.69    79.7 1056.94    96.7 1051.95   123.3 1040.94
   132.6 1039.76   140.1 1036.12  149.251034.711   159.7 1033.73   162.4 1033.78
  168.82 1034.71   171.8 1035.94   177.3 1039.74     181  1041.5   192.2 1044.07
   205.8 1052.08   210.8 1055.38   218.2 1061.11   221.9 1064.54   229.3 1076.23
   236.8 1084.24   244.5 1090.92   247.9 1093.01   252.1 1094.81   273.2 1100.98
#Mann= 3, -1 ,  0
       0     0.1       0  149.25   0.045       0  168.82     0.1       0
Bank Sta=149.25,168.82
XS Rating Curve= 0 ,0
Exp/Cntr(USF)=0,0
Exp/Cntr=0.3,0.1

Type RM Length L Ch R = 1 ,7       ,,,
XS GIS Cut Line= 3
1682635.68472652510728.1906089421682717.62424302510599.291045992
1682719.99179302510462.762329385
#Sta/Elev= 30
       0 1084.67    11.2 1082.71    22.9 1078.59    33.7 1074.29    43.2 1070.37
    57.9 1063.07    69.6  1058.3    87.4 1049.87    92.9 1046.42   108.4 1031.34
  111.371029.277   112.3 1028.79   116.2 1028.48     124 1028.57  128.181029.281
   136.3 1031.26   147.3 1032.39   150.2 1033.48   154.7 1036.73   161.3 1042.13
   164.6 1044.31   177.7 1049.44   194.1 1056.74   210.5 1064.99     217 1068.81
   233.8 1077.64   256.4 1088.36   269.6 1093.35   272.8 1094.08   289.3 1095.48
#Mann= 3, -1 ,  0
       0     0.1       0  111.37   0.045       0  128.18     0.1       0
Bank Sta=111.37,128.18
XS Rating Curve= 0 ,0
Exp/Cntr(USF)=0,0
Exp/Cntr=0.3,0.1
LCMann Table=0

Chan Stop Cuts=-1
Use User Specified Reach Order=0
Composite Channel Slope=5